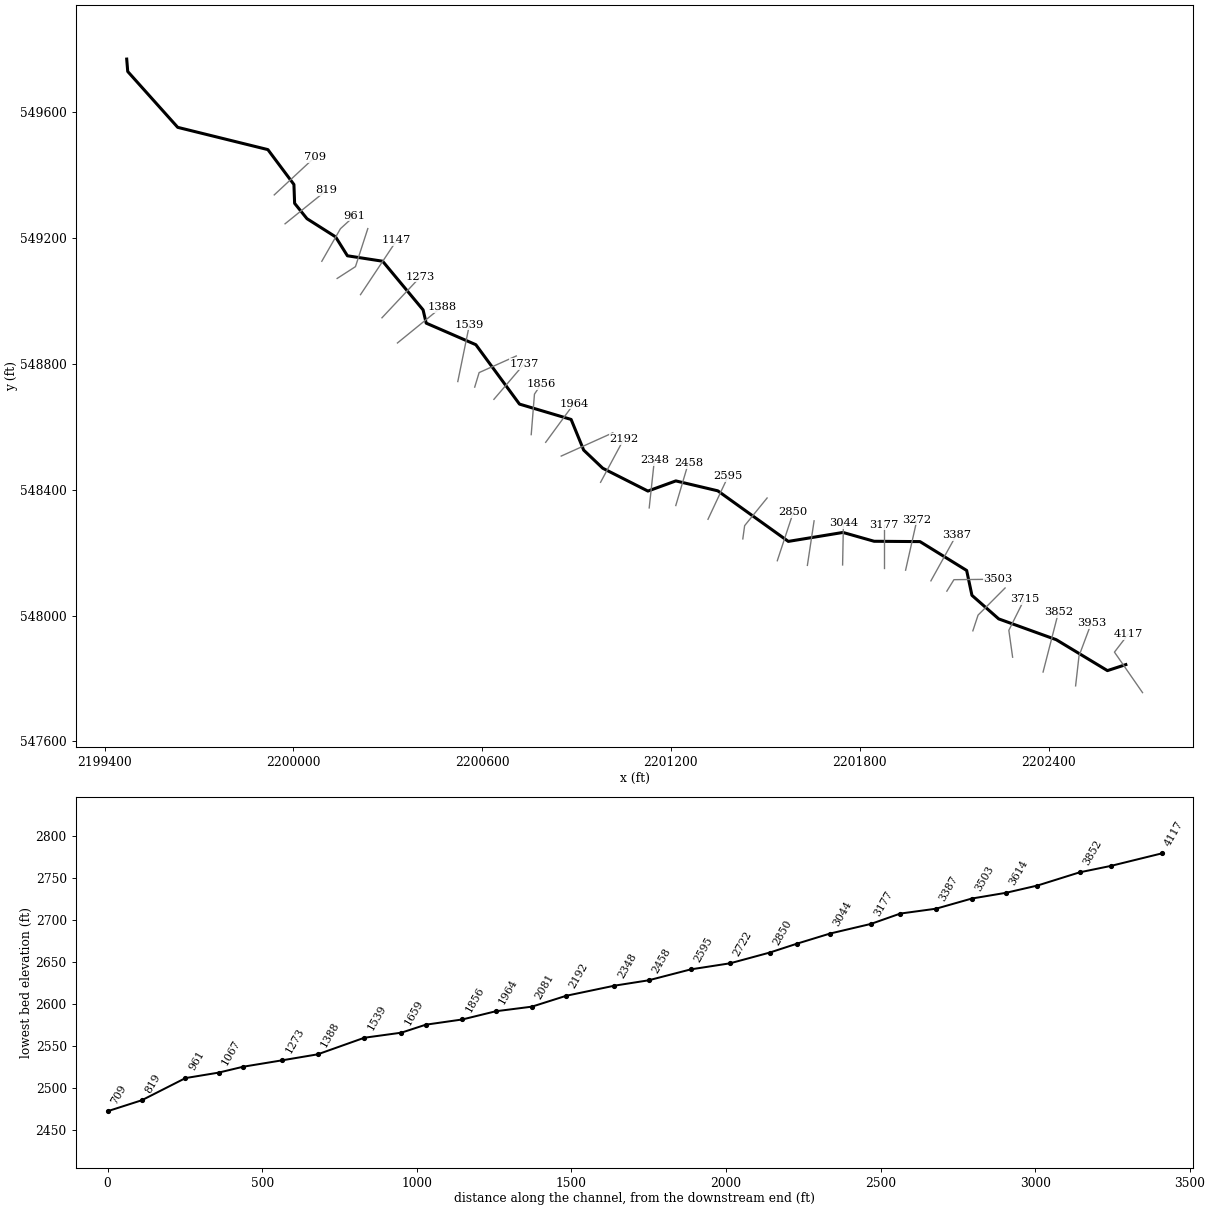
--- BIGRN.prj (project) ---

Proj Title=BIGRN
Current Plan=p01
Default Exp/Contr=0,0
English Units
Geom File=g01
Flow File=f01
Plan File=p01
BEGIN DESCRIPTION:
----------MODEL BY WOOD PLC 2022----------
AFH study
Randolph County, WV
HEC-RAS Version: RAS 6.2
Vertical Datum: NAVD88
Projection: NAD 1983 StatePlane West Virginia S FIPS 4702 (US Feet)
Terrain: 1-meter LIDAR (FEMA Region III 3DEP collected 2016-2018)
Land Use: 2019 NLCD
Hydrologic Method:
WV SIR2010-5033 regression equations
Additional Model Notes:
None
END DESCRIPTION:
DSS Export Rating Curves= 0
DSS Export Rating Curve Sorted= 0
DSS Export Volume Flow Curves= 0
DXF OffsetX= 0
DXF OffsetY= 0
DXF ScaleX= 0
DXF ScaleY= 0

--- BIGRN.p01 (plan) ---

Plan Title=Floodplain
Program Version=6.20
Short Identifier=Floodplain
Geom File=g01
Flow File=f01
Subcritical Flow
K Sum by GR= 0
Std Step Tol= 0.01
Critical Tol= 0.01
Num of Std Step Trials= 20
Max Error Tol= 0.3
Flow Tol Ratio= 0.001
Split Flow NTrial= 30
Split Flow Tol= 0.02
Split Flow Ratio= 0.02
Log Output Level= 0
Friction Slope Method= 1
Unsteady Friction Slope Method= 2
Unsteady Bridges Friction Slope Method= 1
Parabolic Critical Depth
Global Vel Dist= 0 , 0 , 0
Global Log Level= 0
CheckData=True
Encroach Param=-1 ,0,0, 0
Mapping Interval=1HOUR
Computation Time Step Use Courant=        0
Computation Time Step Use Time Series=    0
Computation Time Step Count To Double=0
Computation Time Step Max Doubling=0
Computation Time Step Max Halving=0
Computation Time Step Residence Courant=0
Run HTab= 0
Run UNet= 0
Run Sediment= 0
Run PostProcess= 0
Run WQNet= 0
Run RASMapper=-1
UNET Theta= 0
UNET Theta Warmup= 0
UNET ZTol= 0
UNET ZSATol= 0
UNET MxIter= 0
UNET Max Iter WO Improvement= 0
UNET MaxInSteps= 0
UNET DtIC= 0
UNET DtMin= 0
UNET MaxCRTS= 0
UNET WFStab= 0
UNET SFStab= 0
UNET WFX= 1
UNET SFX= 1
UNET Gravity=32.174
UNET 1D Methodology=Finite Difference
UNET DSS MLevel= 1
UNET Pardiso=0
UNET DZMax Abort= 0
UNET Use Existing IB Tables= 0
UNET Froude Reduction=False
UNET Froude Limit= 0
UNET Froude Power= 0
UNET D1 Cores= 0
UNET WindReference=Eulerian
UNET WindDragFormulation=Hsu (1988)
UNET D2 Coriolis=0
UNET D2 Cores= 0
UNET D2 Theta= 1
UNET D2 Theta Warmup= 1
UNET D2 Z Tol= 0.01
UNET D2 Volume Tol= 0.01
UNET D2 Max Iterations= 20
UNET D2 Equation= 0
UNET D2 RampUpFraction=0.1
UNET D2 TimeSlices= 1
UNET D2 Turbulence Formulation=Non-Conservative (original)
UNET D2 Eddy Viscosity=0.3
UNET D2 Transverse Eddy Viscosity=0.1
UNET D2 Smagorinsky Mixing=0
UNET D2 BCVolumeCheck=0
UNET D2 Cores=0
UNET D2 SolverType=PARDISO (Direct)
UNET D2 Minimum Iterations= 2147483647
UNET D2 Maximum Iterations= 2147483647
UNET D2 Restart Number= 10
UNET D2 Relaxation Coeff=1.3
UNET D2 SOR Precondition Iterations= 10
UNET D2 ILUT Maximum Fill= 8
UNET D2 ILUT Tolerance=1E-08
UNET D1D2 MaxIter= 0
UNET D1D2 ZTol=0.01
UNET D1D2 QTol=0.1
UNET D1D2 MinQTol=1
Write IC File= 0
Write IC File at Fixed DateTime=0
Write IC File at Sim End=0
Echo Input=False
Echo Parameters=False
Echo Output=False
Write Detailed= 0
HDF Write Warmup=0
HDF Write Time Slices=0
HDF Flush=0
HDF Compression= 1
HDF Chunk Size= 1
HDF Spatial Parts= 1
HDF Use Max Rows=0
HDF Fixed Rows= 1
Calibration Method= 0
Calibration Iterations= 20
Calibration Max Change=0.05
Calibration Tolerance=0.2
Calibration Maximum=1.5
Calibration Minimum=0.5
Calibration Optimization Method= 1
WQ AD Non Conservative
WQ ULTIMATE=-1
WQ Max Comp Step=1HOUR
WQ Output Interval=15MIN
WQ Output Selected Increments= 0
WQ Output face flow=0
WQ Output face velocity=0
WQ Output face area=0
WQ Output face dispersion=0
WQ Output cell volume=0
WQ Output cell surface area=0
WQ Output cell continuity=0
WQ Output cumulative cell continuity=0
WQ Output face conc=0
WQ Output face dconc_dx=0
WQ Output face courant=0
WQ Output face peclet=0
WQ Output face adv mass=0
WQ Output face disp mass=0
WQ Output cell mass=0
WQ Output cell source sink temp=0
WQ Output nsm pathways=0
WQ Output nsm derived pathways=0
WQ Create Restart=0
WQ Fixed Restart=0
WQ System Summary=0
WQ Write To DSS=0
Sorting and Armoring Iterations= 10
XS Update Threshold= 0.02
Bed Roughness Predictor= 0
Hydraulics Update Threshold= 0.02
Energy Slope Method= 1
Volume Change Method= 1
Sediment Retention Method= 0
Sediment TS Multiplier= 1
Warm Up Method= 0
XS Weighting Method= 0
Number of US Weighted Cross Sections= 1
Number of DS Weighted Cross Sections= 1
Upstream XS Weight=0
Main XS Weight=1
Downstream XS Weight=0
Number of DS XS's Weighted with US Boundary= 1
Upstream Boundary Weight= 1
Weight of XSs Associated with US Boundary= 0
Number of US XS's Weighted with DS Boundary= 1
Downstream Boundary Weight= 0.5
Weight of XSs Associated with DS Boundary= 0.5
Percentile Method= 0
Sediment Output Level= 3
Mass or Volume Output= 0
Output Increment Type= 1
Profile and TS Output Increment= 1
Transport Output Increment 1
XS Output Flag= 0
XS Output Increment= 10
Read HDF5 Sediment Hotstart= 0
Sediment Hotstart Type= 0
Write Gradation File= 0
Read Gradation Hotstart= 0
Write HDF5 File= 1
Write Binary Output= 1
Write DSS Sediment File= 0
DSS Sediment Output Type= 1
SV Curve= 0
Specific Gage Flag= 0
Subcell Erosion Methods= 0
Subcell Deposition Methods= 0
Advection Scheme= 1
Matrix Solver= 0
Implicit Weighting Factor= 1
Maximum Outer Loop Convergence Iterations= 5
Convergence Maximum Absolute= 0.001
Convergence RMSE= 0.0001
Grain Fractions Max Abs Error= 0.001
Max Subgrid Regions= 1
Max Subgrid Length Scale= 3.402823E+38
Initial Layer Thickness= 3.402823E+38
Min Layer Thickness= 3.402823E+38
Max Layer Thickness= 3.402823E+38
Number of Layers= 5

--- BIGRN.f01 (steady flow) ---

Flow Title=Flow
Program Version=6.20
Number of Profiles= 1
Profile Names=P100yr
River Rch & RM=BIGRN,Main,4117
     402
River Rch & RM=BIGRN,Main,1067
     450
Boundary for River Rch & Prof#=BIGRN,Main            , 1
Up Type= 0
Dn Type= 3
Dn Slope=0.19395
DSS Import GetInterval= 0
DSS Import GetPeak= 0
DSS Import FillOption= 0

--- BIGRN.g01 (geometry) ---

Geom Title=Geometry
Program Version=6.20

River Reach=BIGRN           ,Main
Reach XY= 30
     2202645.681      547843.985     2202587.167      547824.916
     2202424.546      547923.232     2202241.611      547989.395
     2202156.618      548064.2972202139.82303856548143.348378319
     2201991.514      548235.131     2201845.681      548236.172
2201746.77106404548264.250487531     2201573.068      548235.742
     2201348.806      548396.5892201215.58981825548428.095091001
 2201126.8465455548395.780180733     2200983.181      548468.464
     2200922.641      548526.135      2200882.78       548623.54
     2200718.674      548672.328     2200580.056      548861.172
 2200422.2384545548929.7470907472200412.34886324548971.901743908
     2200283.807      549126.6022200171.85374801549143.894763771
2200134.14707084549204.1642913122200043.32640281 549261.87625616
     2200004.072      549310.6942200001.86821732549370.595892176
     2199919.118      549481.485     2199632.506      549552.281
2199473.70378656549729.8172661282199470.45517787549769.315080426

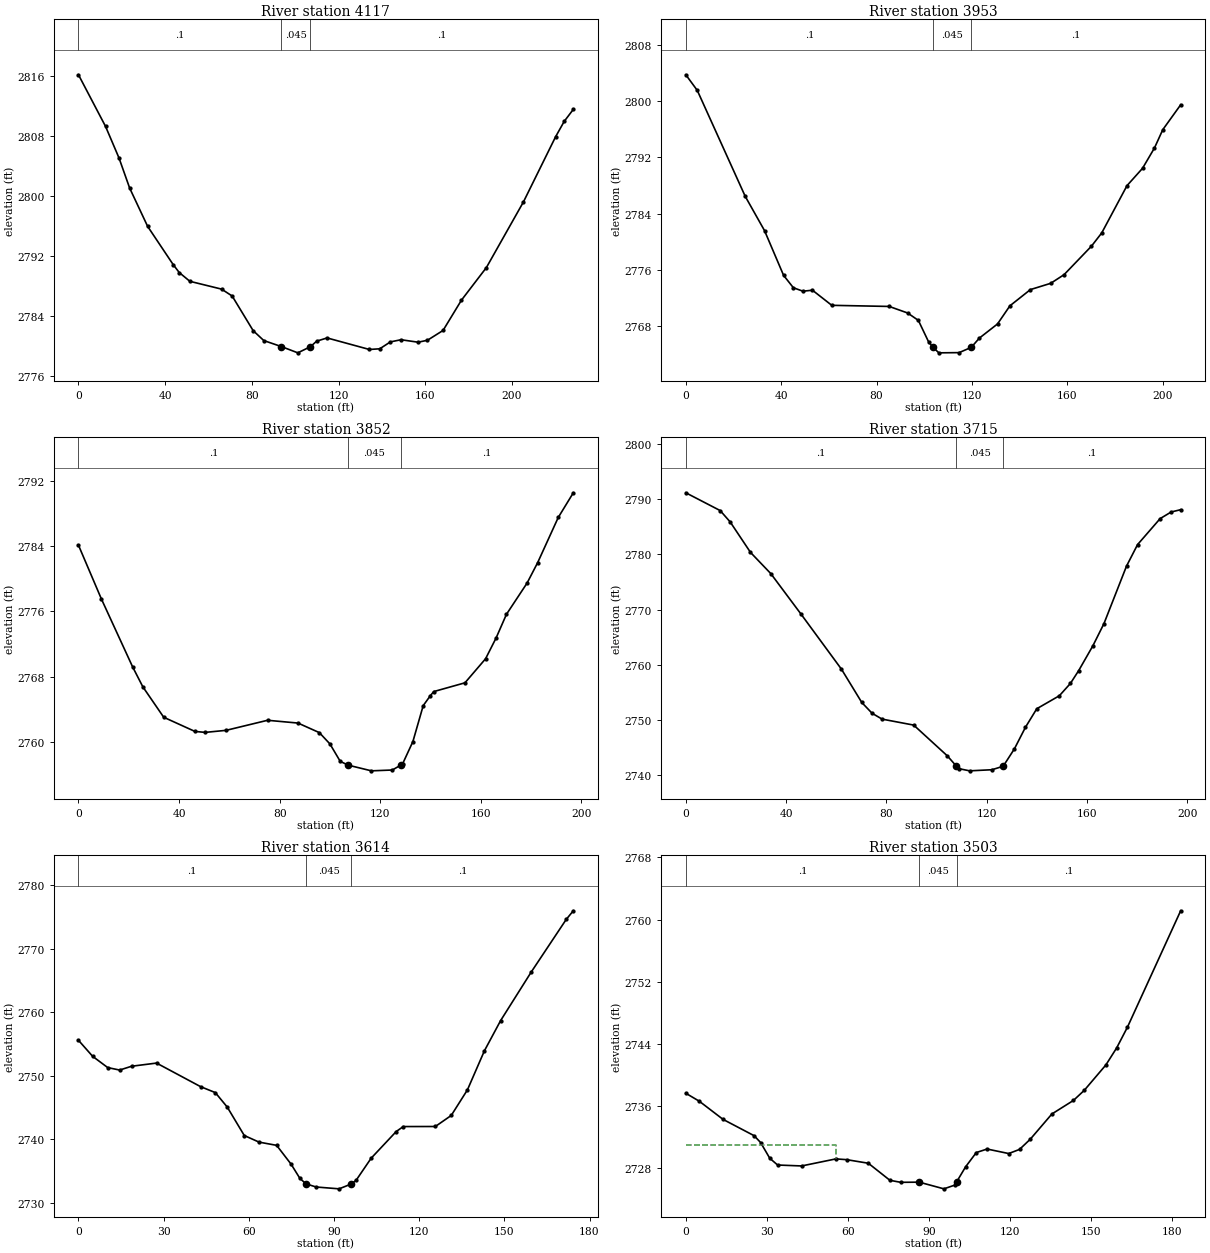
Type RM Length L Ch R = 1 ,4117    ,163.9,163.9,163.9
XS GIS Cut Line= 3
2202698.80609833547754.9295340262202609.52782374547883.689226683
2202653.19261717547940.515750471
#Sta/Elev= 30
       0 2816.17    12.5 2809.27    18.7 2805.06    23.6 2801.05    31.9 2795.93
    43.7 2790.82    46.5 2789.76    51.4 2788.59      66 2787.55    70.9 2786.63
    80.6    2782    85.5 2780.68   93.66 2779.87   101.2 2779.04     107 2779.86
   109.9  2780.6   114.7 2781.03   134.2 2779.49     139 2779.58   143.9  2780.5
   148.8 2780.79   156.7 2780.46     161 2780.72   168.2 2782.03   176.7 2786.08
   188.2 2790.43   205.3  2799.2   220.1 2807.88   224.1 2809.95   228.3 2811.55
#Mann= 3 ,-1,0
       0      .1       0   93.66    .045       0     107      .1       0
Bank Sta=93.66,107
XS Rating Curve= 0 ,0
Exp/Cntr(USF)=0,0
Exp/Cntr=0.3,0.1

Type RM Length L Ch R = 1 ,3953    ,101.4,101.4,101.4
XS GIS Cut Line= 3
2202486.09440071 547776.398362592202496.82757661547871.345687905
2202536.04495011547976.200560209
#Sta/Elev= 30
       0 2803.76     4.8 2801.54    24.9 2786.47      33 2781.59      41 2775.22
    45.1 2773.46    49.1 2772.97    53.1 2773.11    61.2 2770.96    85.3  2770.8
      93 2769.87    97.5 2768.82   101.8 2765.76   103.72764.968   106.1  2764.2
   114.6 2764.23  119.69 2764.98   123.1  2766.3   130.7 2768.31   135.9 2770.89
   144.5  2773.2     153 2774.09   158.6 2775.32   170.1 2779.38   174.4 2781.26
     185 2787.99   191.5 2790.45   196.5 2793.34     200 2795.95   207.5 2799.49
#Mann= 3 ,0,0
       0      .1       0   103.7    .045       0  119.69      .1       0
Bank Sta=103.7,119.69
XS Rating Curve= 0 ,0
Exp/Cntr(USF)=0,0
Exp/Cntr=0.3,0.1

Type RM Length L Ch R = 1 ,3852    ,136.4,136.4,136.4
XS GIS Cut Line= 2
2202382.66300017547820.3535625372202431.66617653548010.945148667
#Sta/Elev= 30
       0  2784.1     9.1 2777.54    21.5 2769.25    25.6 2766.79    33.9 2763.07
    46.3 2761.34    50.4 2761.22    58.7 2761.47    75.2  2762.7    87.3 2762.36
    95.8 2761.19     100 2759.81   104.1 2757.68  107.262757.214   116.5 2756.52
   124.8 2756.62  128.192757.215   128.9 2757.37     133  2760.1   137.1 2764.49
   139.9 2765.69   141.3 2766.21   153.7 2767.28   161.9 2770.22   166.1 2772.77
   170.2 2775.65   178.4 2779.47   182.6 2781.96   190.8 2787.49   196.8 2790.51
#Mann= 3 ,-1,0
       0      .1       0  107.26    .045       0  128.19      .1       0
Bank Sta=107.26,128.19
XS Rating Curve= 0 ,0
Exp/Cntr=0.3,0.1

Type RM Length L Ch R = 1 ,3715    ,101.4,101.4,101.4
XS GIS Cut Line= 3
2202285.87938863547867.6303577842202273.90776935547953.082950567
 2202323.4455043548052.571234918
#Sta/Elev= 30
       0 2791.13    13.7 2787.91    17.7 2785.85    25.8 2780.34    33.9  2776.5
      46 2769.14    62.1 2759.19    70.2 2753.17    74.3 2751.22    78.3 2750.16
    90.9 2749.08   104.3 2743.52  107.97 2741.63   108.9  2741.2   113.2  2740.8
   122.1    2741   126.6 2741.63   131.1  2744.8   135.5  2748.7     140 2752.04
     149 2754.39   153.4 2756.61   156.7 2758.93   162.4 2763.45   166.8 2767.45
   175.8 2777.86   180.2 2781.75   189.2 2786.45   193.6 2787.65   197.4 2788.07
#Mann= 3 ,0,0
       0      .1       0  107.97    .045       0   126.6      .1       0
Bank Sta=107.97,126.6
XS Rating Curve= 0 ,0
Exp/Cntr(USF)=0,0
Exp/Cntr=0.3,0.1

Type RM Length L Ch R = 1 ,3614    ,111.2,111.2,111.2
XS GIS Cut Line= 3
2202159.55816452547951.4316927352202176.07074283 548001.38224214
2202261.93615007548087.660463839
#Sta/Elev= 30
       0 2755.57       5 2753.04    10.3 2751.27    14.5 2750.88    18.7 2751.48
    27.5 2751.98      43 2748.27    48.2 2747.33    52.4 2745.05    58.4 2740.57
    63.6 2739.53    69.8 2739.02    74.9 2736.05      78 2733.81   80.14 2732.96
    83.7 2732.46    91.8 2732.17   96.12 2732.94    97.8 2733.52   103.1    2737
   111.9 2741.19   114.4 2741.98   125.7 2741.99   131.3 2743.73     137 2747.76
     143 2753.93   148.7 2758.68   159.5 2766.34   171.8 2774.61   174.3 2775.97
#Mann= 3 ,0,0
       0      .1       0   80.14    .045       0   96.12      .1       0
Bank Sta=80.14,96.12
XS Rating Curve= 0 ,0
Exp/Cntr(USF)=0,0
Exp/Cntr=0.3,0.1

Type RM Length L Ch R = 1 ,3503    ,115.3,115.3,115.3
XS GIS Cut Line= 3
2202076.90009874548077.610580733 2202099.4418314548114.058244202
2202239.89927024548115.553713206
#Sta/Elev= 30
       0 2737.61       5 2736.58    13.8 2734.24    25.3 2732.14    27.7 2731.26
    31.1 2729.23      34 2728.36    42.9 2728.24    55.6 2729.15    59.6 2729.05
    67.6 2728.59    75.6 2726.39    79.6 2726.1386.453532726.151    95.6 2725.29
    99.6 2725.77   100.32726.179   103.6 2728.11   107.6 2729.97   111.6 2730.42
   119.6 2729.84   123.6 2730.37   127.6 2731.69   135.6 2734.94   143.6 2736.69
   147.6 2737.99   155.6 2741.26   159.6 2743.46   163.6 2746.14   183.3 2761.13
#Mann= 3 ,-1,0
       0      .1       086.45353    .045       0   100.3      .1       0
#XS Ineff= 2 , 0
            55.6    2731
Permanent Ineff=
       F       F
Bank Sta=86.45353,100.3
XS Rating Curve= 0 ,0
Exp/Cntr(USF)=0,0
Exp/Cntr=0.3,0.1

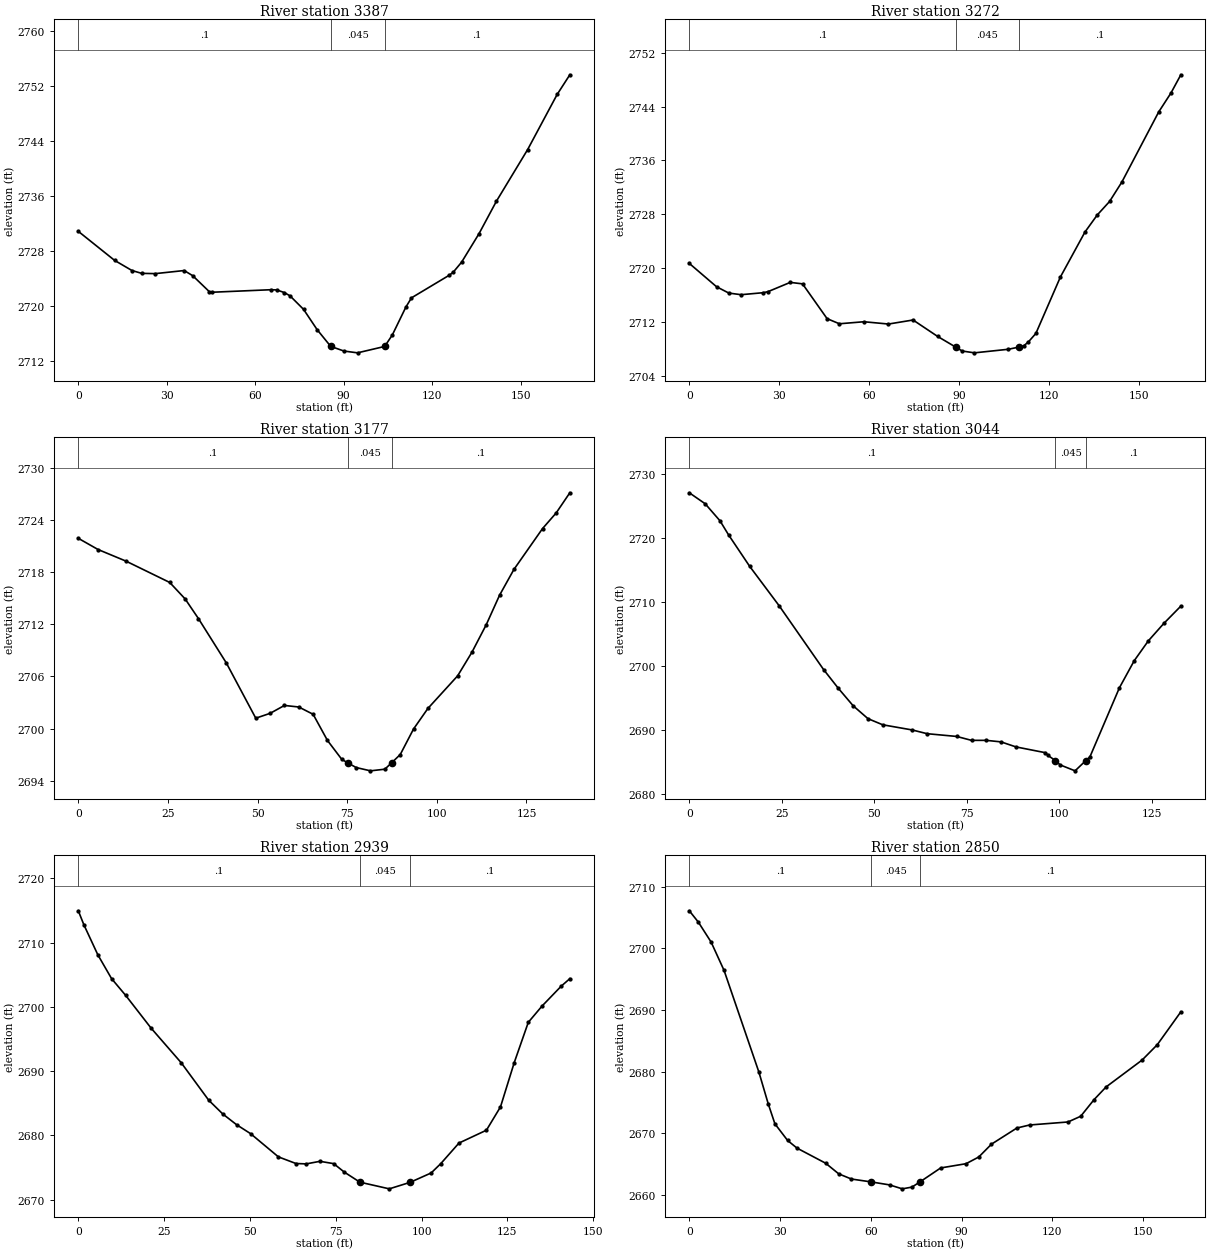
Type RM Length L Ch R = 1 ,3387    ,115.9,115.9,115.9
XS GIS Cut Line= 2
2202026.21909462548110.3652590232202107.13072836548256.088762658
#Sta/Elev= 30
       0 2730.89    12.3 2726.67    18.2 2725.19    21.5 2724.78    26.1 2724.74
    35.9 2725.19    38.8 2724.44    44.4 2722.13    45.2 2722.03    65.3  2722.4
    67.3 2722.37    69.9 2721.98    71.8 2721.51    76.4 2719.54      81 2716.59
    85.6 2714.16    90.1 2713.48    94.7 2713.22   103.9 2714.15   106.5 2715.82
   111.1 2719.88     113 2721.22   125.7 2724.48   127.1 2724.92     130 2726.41
   135.9 2730.55   141.8 2735.27   152.4 2742.79   162.4  2750.8   166.7 2753.66
#Mann= 3 ,0,0
       0      .1       0    85.6    .045       0   103.9      .1       0
Bank Sta=85.6,103.9
XS Rating Curve= 0 ,0
Exp/Cntr(USF)=0,0
Exp/Cntr=0.3,0.1

Type RM Length L Ch R = 1 ,3272    ,94.5,94.5,94.5
XS GIS Cut Line= 2
2201945.77825349548144.2855803532201981.84031852548304.408685291
#Sta/Elev= 30
       0 2720.69     9.1 2717.22    13.2 2716.28    17.3 2716.04    24.5 2716.33
    26.2 2716.48    33.7 2717.87    37.8 2717.65      46 2712.48    50.1 2711.72
    58.3 2712.02    66.5 2711.68    74.7 2712.28    82.9 2709.84   88.882708.266
    91.1 2707.67    95.2  2707.4   106.5 2707.93  109.952708.246   111.6 2708.42
   113.2 2709.02   115.7 2710.28   123.9 2718.68   132.1 2725.36   136.2 2727.89
   140.3 2729.89   144.4 2732.77   156.7 2743.19   160.8 2746.01   164.1 2748.72
#Mann= 3 ,-1,0
       0      .1       0   88.88    .045       0  109.95      .1       0
Bank Sta=88.88,109.95
XS Rating Curve= 0 ,0
Exp/Cntr(USF)=0,0
Exp/Cntr=0.3,0.1

Type RM Length L Ch R = 1 ,3177    ,133,133,133
XS GIS Cut Line= 2
2201875.95463194548151.6467048122201875.95463194548288.701104832
#Sta/Elev= 30
       0 2721.93     5.5 2720.64    13.3  2719.3    25.5 2716.84    29.8 2714.94
    33.5 2712.68    41.3 2707.55    49.5 2701.19    53.5 2701.75    57.5 2702.66
    61.5 2702.48    65.5 2701.64    69.5 2698.62    73.5 2696.44   75.12 2696.05
    77.5  2695.5    81.5 2695.12    85.5 2695.31   87.38 2696.04    89.8    2697
    93.5 2699.94    97.5 2702.31   105.8 2706.07   109.8  2708.8   113.8 2711.98
   117.5 2715.37   121.5 2718.34   129.5 2723.06   133.3 2724.86   137.1 2727.18
#Mann= 3 ,0,0
       0      .1       0   75.12    .045       0   87.38      .1       0
Bank Sta=75.12,87.38
XS Rating Curve= 0 ,0
Exp/Cntr(USF)=0,0
Exp/Cntr=0.3,0.1

Type RM Length L Ch R = 1 ,3044    ,105.3,105.3,105.3
XS GIS Cut Line= 2
2201745.60264475548160.9163760772201748.20036946548293.815203757
#Sta/Elev= 30
       0 2726.99     4.3 2725.27     8.3 2722.61    10.6 2720.43    16.3 2715.52
    24.3 2709.34    36.3 2699.39    40.3 2696.45    44.3 2693.73    48.3 2691.72
    52.3 2690.76    60.3 2689.95    64.3 2689.37    72.3 2688.94    76.3 2688.33
    80.3 2688.33    84.3 2688.09    88.3 2687.31    96.3  2686.4      97 2685.97
   98.952685.183   100.3 2684.49   104.3 2683.57  107.222685.179   108.3 2685.73
   116.3 2696.55   120.3 2700.77   124.1 2703.86   128.3 2706.59   132.9 2709.29
#Mann= 3 ,-1,0
       0      .1       0   98.95    .045       0  107.22      .1       0
Bank Sta=98.95,107.22
XS Rating Curve= 0 ,0
Exp/Cntr(USF)=0,0
Exp/Cntr=0.3,0.1

Type RM Length L Ch R = 1 ,2939    ,89.1,89.1,89.1
XS GIS Cut Line= 2
2201633.67099788548159.5617776152201654.97499713548301.130288806
#Sta/Elev= 30
       0 2714.94     1.6 2712.79     5.7 2708.08     9.7 2704.38    13.8 2701.78
    21.2 2696.69      30 2691.29      38 2685.47    42.1 2683.33    46.1 2681.67
    50.2 2680.27    58.3 2676.66    63.4 2675.63    66.4 2675.57    70.4 2675.97
    74.4 2675.61    77.5 2674.29   82.042672.726    90.6 2671.69   96.692672.705
   102.8 2674.16   105.6 2675.61   110.9 2678.81   118.9 2680.81     123 2684.44
     127 2691.32   131.1 2697.59   135.1 2700.12   140.7 2703.22   143.2 2704.38
#Mann= 3 ,-1,0
       0      .1       0   82.04    .045       0   96.69      .1       0
Bank Sta=82.04,96.69
XS Rating Curve= 0 ,0
Exp/Cntr(USF)=0,0
Exp/Cntr=0.3,0.1

Type RM Length L Ch R = 1 ,2850    ,128.2,128.2,128.2
XS GIS Cut Line= 2
2201538.06896037 548174.300603642201588.93824328548328.604095142
#Sta/Elev= 30
       0 2706.11       3 2704.26     7.2 2701.04    11.5 2696.42      23 2679.94
    26.1 2674.77    28.3 2671.54    32.5 2668.84    35.6  2667.6    45.1 2665.14
    49.4 2663.42    53.6 2662.58   60.212662.108    66.2 2661.63    70.4 2660.99
    73.6 2661.27   76.232662.107    83.1 2664.38    91.5 2665.07    95.7 2666.16
    99.9 2668.24   108.3 2670.86   112.5 2671.35   125.2 2671.84   129.4 2672.77
   133.8 2675.46   137.8 2677.53   149.7 2681.89   154.7 2684.37   162.5 2689.71
#Mann= 3 ,-1,0
       0      .1       0   60.21    .045       0   76.23      .1       0
Bank Sta=60.21,76.23
XS Rating Curve= 0 ,0
Exp/Cntr(USF)=0,0
Exp/Cntr=0.3,0.1

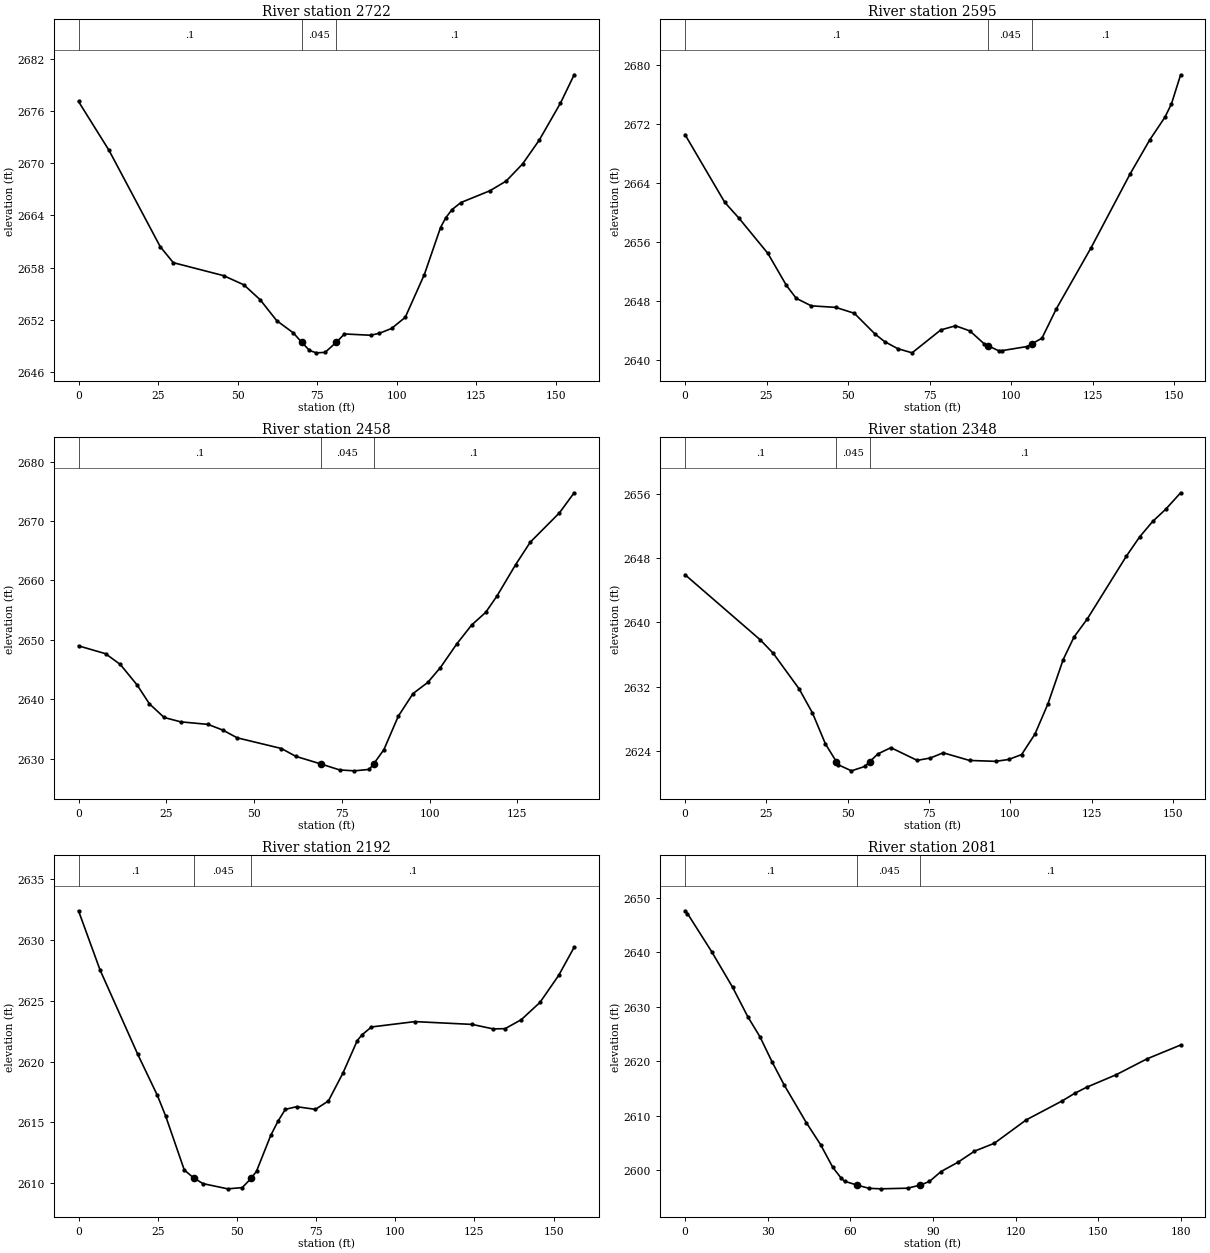
Type RM Length L Ch R = 1 ,2722    ,127,127,127
XS GIS Cut Line= 3
2201428.46375959548243.704328922  2201434.243162548285.811403626
2201505.66006322548373.740883157
#Sta/Elev= 30
       0 2677.09     9.6 2671.47    25.7  2660.4    29.8 2658.57    45.6 2657.08
      52 2656.02    57.1 2654.31    62.3 2651.91    67.5 2650.51    70.12649.447
    72.6 2648.49    74.7 2648.21    77.5 2648.26   81.08 2649.44    83.6 2650.38
    91.8 2650.23    94.6 2650.46    98.4 2651.01   102.7 2652.29   108.7  2657.2
   113.8 2662.61   115.4 2663.71   117.4 2664.67   120.2 2665.48   129.3 2666.83
   134.4 2667.94   139.6 2669.92   144.8 2672.64   151.5 2676.91   155.8 2680.16
#Mann= 3 ,0,0
       0      .1       0    70.1    .045       0   81.08      .1       0
Bank Sta=70.1,81.08
XS Rating Curve= 0 ,0
Exp/Cntr(USF)=0,0
Exp/Cntr=0.3,0.1

Type RM Length L Ch R = 1 ,2595    ,136.8,136.8,136.8
XS GIS Cut Line= 2
2201317.80752647548306.1364940122201382.22498755548443.688678066
#Sta/Elev= 30
       0 2670.61    12.2  2661.4    16.6 2659.23    25.4 2654.48    31.1 2650.12
    34.1 2648.38    38.7 2647.36    46.2 2647.15    51.9 2646.35    58.2 2643.55
    61.2  2642.5    65.2 2641.55    69.6 2640.98    78.4 2644.09    82.9 2644.65
    87.3 2643.96    91.7  2642.2    92.8 2641.96    96.1 2641.27    97.3 2641.29
   104.9 2641.84   106.3  2642.2   109.4 2642.97   113.8 2646.95   124.4  2655.2
   136.4 2665.25   142.4 2669.86   147.1 2672.97   149.1 2674.79   151.9 2678.72
#Mann= 3 ,-1,0
       0      .1       0    92.8    .045       0   106.3      .1       0
Bank Sta=92.8,106.3
XS Rating Curve= 0 ,0
Exp/Cntr=0.3,0.1

Type RM Length L Ch R = 1 ,2458    ,110.1,110.1,110.1
XS GIS Cut Line= 2
2201215.45149932548349.7976445992201255.49450174548485.200786788
#Sta/Elev= 30
       0 2648.98     7.7 2647.66    11.9 2645.85    16.7 2642.39    20.2 2639.22
    24.4 2636.92    29.1 2636.19    36.9 2635.76    41.1  2634.8    45.2  2633.5
    57.8  2631.7    61.9 2630.38    69.1 2629.09    74.4 2628.09    78.6 2627.94
    82.8 2628.18   84.05 2629.08      87 2631.51    91.1 2637.14    95.3 2640.95
    99.5 2642.83   103.1 2645.33   107.8 2649.34     112 2652.49     116 2654.62
   119.2 2657.36   124.5 2662.63   128.7 2666.44     137 2671.37   141.2 2674.75
#Mann= 3 ,0,0
       0      .1       0    69.1    .045       0   84.05      .1       0
Bank Sta=69.1,84.05
XS Rating Curve= 0 ,0
Exp/Cntr(USF)=0,0
Exp/Cntr=0.3,0.1

Type RM Length L Ch R = 1 ,2348    ,156.1,156.1,156.1
XS GIS Cut Line= 2
2201130.93638842548342.235284408 2201147.3276018548493.712704637
#Sta/Elev= 30
       0 2645.94    23.1 2637.86    27.1 2636.19    35.1 2631.75    39.2 2628.76
    43.2  2624.9   46.552622.714    47.2 2622.31    51.2 2621.57    55.3 2622.12
   56.872622.728    59.3 2623.67    63.3 2624.45    71.4 2622.87    75.4 2623.16
    79.4 2623.81    87.5 2622.86    95.5 2622.75    99.5 2622.98   103.5 2623.59
   107.6 2626.13   111.6 2629.89   116.3  2635.4   119.6 2638.18   123.7 2640.44
   135.7 2648.23   139.8 2650.63   143.8 2652.55   147.8 2654.06   152.4 2656.11
#Mann= 3 ,-1,0
       0      .1       0   46.55    .045       0   56.87      .1       0
Bank Sta=46.55,56.87
XS Rating Curve= 0 ,0
Exp/Cntr(USF)=0,0
Exp/Cntr=0.3,0.1

Type RM Length L Ch R = 1 ,2192    ,110.9,110.9,110.9
XS GIS Cut Line= 2
2200976.40262444548423.6749827452201050.52244928548561.510503371
#Sta/Elev= 30
       0 2632.41     6.8 2627.54    18.7  2620.6    24.9 2617.22    27.5 2615.53
    33.4 2611.08    36.4 2610.42    39.3 2609.96    47.1 2609.53    51.7 2609.63
   54.56 2610.41    56.2 2610.98    60.7 2613.93      63  2615.1    65.3 2616.07
    68.9 2616.29    74.8 2616.07    78.9 2616.76    83.5 2619.06      88 2621.72
    89.5  2622.2    92.5 2622.85   106.2 2623.29   124.3 2623.06   130.9 2622.69
   134.7 2622.71   139.8 2623.45   145.7 2624.87   151.6 2627.09   156.5 2629.41
#Mann= 3 ,-1,0
       0      .1       0    36.4    .045       0   54.56      .1       0
Bank Sta=36.4,54.56
XS Rating Curve= 0 ,0
Exp/Cntr(USF)=0,0
Exp/Cntr=0.3,0.1

Type RM Length L Ch R = 1 ,2081    ,117,117,117
XS GIS Cut Line= 2
2200851.34914746548507.0799530562201015.23648724548580.973741018
#Sta/Elev= 30
       0 2647.62      .9 2647.12     9.7  2640.1    17.3 2633.56    22.8 2628.16
    27.2 2624.49    31.6 2619.88      36 2615.63      44 2608.74    49.2 2604.69
    53.6 2600.54    56.6 2598.58    57.9 2597.97    62.3 2597.29    66.7 2596.68
    71.1 2596.58    80.8  2596.7    85.4 2597.28    88.7 2597.94    92.9 2599.76
      99 2601.45     105 2603.49   112.2 2604.94   123.8 2609.24   136.9 2612.74
   141.3 2614.09   145.7 2615.23   156.4 2617.52   167.6 2620.44   179.8 2622.98
#Mann= 3 ,0,0
       0      .1       0    62.3    .045       0    85.4      .1       0
Bank Sta=62.3,85.4
XS Rating Curve= 0 ,0
Exp/Cntr(USF)=0,0
Exp/Cntr=0.3,0.1

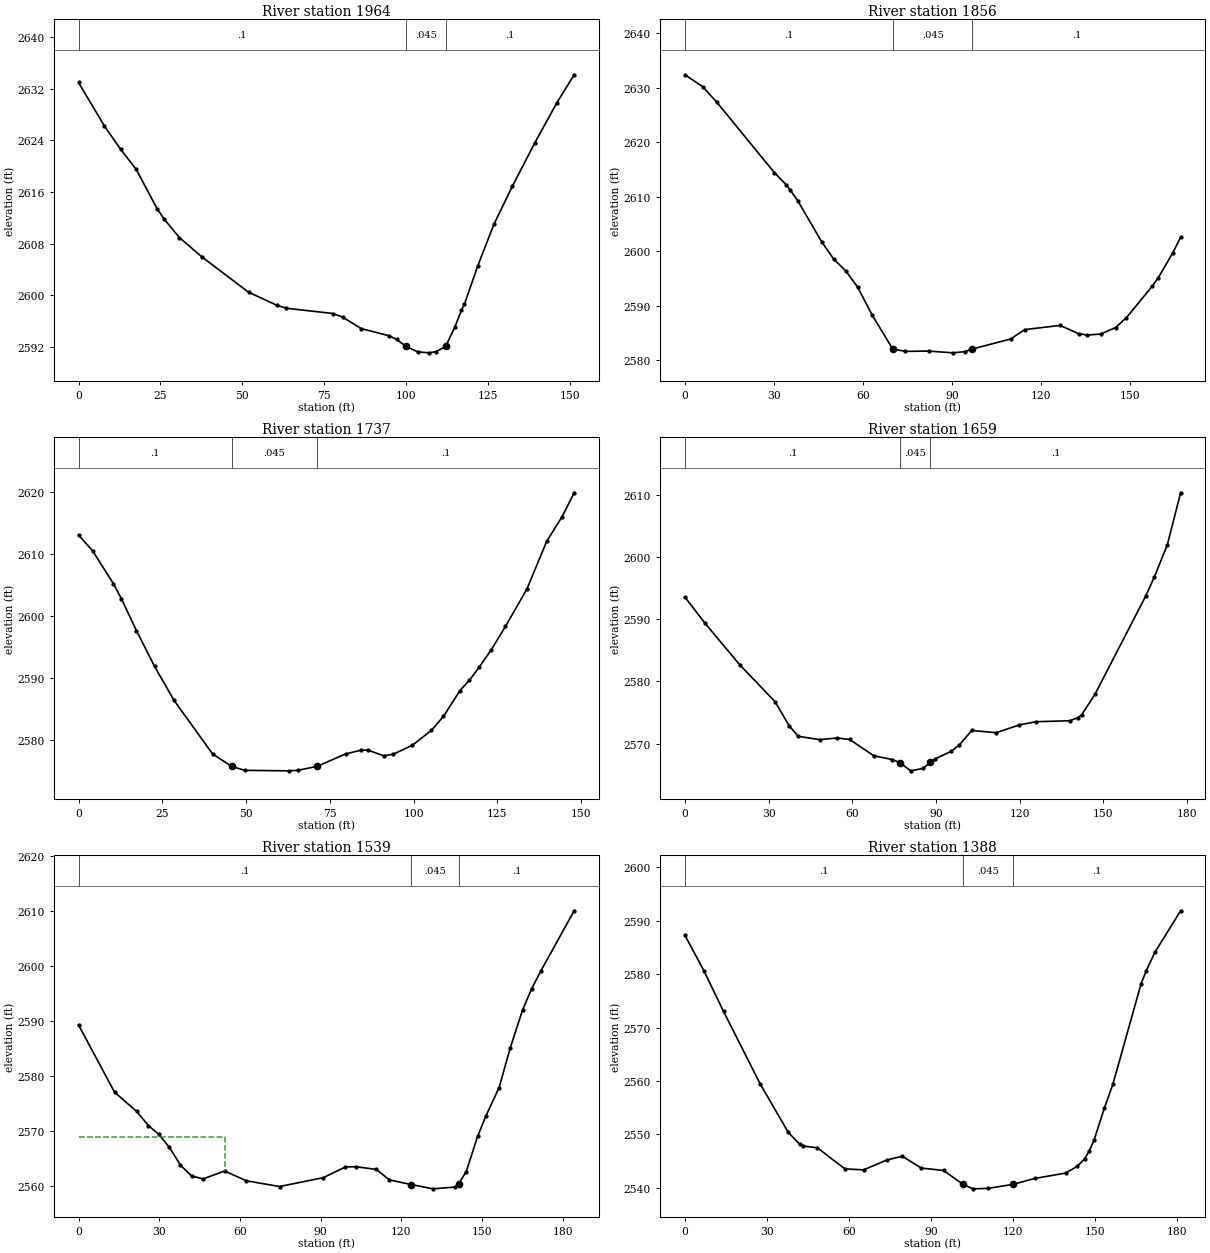
Type RM Length L Ch R = 1 ,1964    ,107.7,107.7,107.7
XS GIS Cut Line= 2
2200801.98169225 548550.799344352200891.28554447 548672.88562334
#Sta/Elev= 30
       0 2632.96     7.9 2626.23    12.9 2622.58    17.6 2619.51      24  2613.4
    26.2 2611.77    30.8 2608.94    37.6 2605.97    51.9 2600.48    60.5 2598.47
    63.4    2598    77.7 2597.18    80.6 2596.63    86.3 2594.85    94.9 2593.72
    97.1 2593.16   99.952592.101   103.5 2591.25     107 2591.09   109.2 2591.29
  112.092592.101   114.9 2595.11   116.9 2597.69   117.8 2598.62   121.9 2604.59
   126.8 2610.99   132.4 2616.86   139.2 2623.52     146  2629.8   151.3 2634.15
#Mann= 3 ,-1,0
       0      .1       0   99.95    .045       0  112.09      .1       0
Bank Sta=99.95,112.09
XS Rating Curve= 0 ,0
Exp/Cntr(USF)=0,0
Exp/Cntr=0.3,0.1

Type RM Length L Ch R = 1 ,1856    ,118.6,118.6,118.6
XS GIS Cut Line= 3
2200755.98900769548575.1943386072200766.30936914548703.992449469
2200787.36290649548735.366348269
#Sta/Elev= 30
       0  2632.4       6  2630.2    10.7 2627.38    30.1 2614.45    34.1 2612.21
    35.5 2611.22    38.1 2609.18    46.1 2601.69    50.1 2598.58    54.2 2596.37
    58.2 2593.41      63 2588.34   69.99 2582.07    74.2 2581.62    82.2 2581.67
    90.3 2581.35    94.3 2581.57   96.87 2582.06   109.8  2583.9   114.4 2585.61
   126.4 2586.39   132.6 2584.87   135.5 2584.62   140.1  2584.8   145.1    2586
   148.7 2587.79   157.4 2593.56   159.5 2595.17   164.4 2599.74     167 2602.61
#Mann= 3 ,0,0
       0      .1       0   69.99    .045       0   96.87      .1       0
Bank Sta=69.99,96.87
XS Rating Curve= 0 ,0
Exp/Cntr(USF)=0,0
Exp/Cntr=0.3,0.1

Type RM Length L Ch R = 1 ,1737    ,78.9,78.9,78.9
XS GIS Cut Line= 2
2200637.43456463548687.4835026072200733.52098791548799.961139269
#Sta/Elev= 30
       0 2613.01     4.2 2610.47    10.4  2605.2    12.8 2602.76    17.3 2597.61
    22.7 2591.88    28.5 2586.42      40 2577.81    45.7  2575.8    49.6 2575.17
    62.7 2575.09    65.4 2575.17    71.2 2575.81    79.7 2577.81    84.3 2578.41
    86.4 2578.41    91.1 2577.51    93.9 2577.76    99.6  2579.2   105.3  2581.6
   108.9 2583.84   113.8 2587.99   116.6 2589.63   119.5 2591.71   123.2 2594.59
   127.4 2598.32   133.8 2604.32   139.7 2611.99   144.3 2615.96   147.9  2619.8
#Mann= 3 ,-1,0
       0      .1       0    45.7    .045       0    71.2      .1       0
Bank Sta=45.7,71.2
XS Rating Curve= 0 ,0
Exp/Cntr(USF)=0,0
Exp/Cntr=0.3,0.1

Type RM Length L Ch R = 1 ,1659    ,119.7,119.7,119.7
XS GIS Cut Line= 3
2200576.41471851548726.2844301952200590.45041007548772.519649479
2200708.51534503548825.359900089
#Sta/Elev= 30
       0 2593.56     7.2 2589.35    19.7 2582.64    32.3 2576.73    37.4 2572.83
    40.6 2571.16    48.3 2570.62    54.6 2570.89      59 2570.65    67.7 2568.03
    74.3 2567.42   77.07 2566.93    80.9  2565.6    85.3 2565.98   88.01 2566.95
    89.6  2567.5    95.5 2568.76    98.4 2569.78   102.8  2572.1   111.6 2571.74
   119.8 2572.98   125.8 2573.51   137.9 2573.66   140.9 2574.16   142.2 2574.61
     147 2577.93   165.2 2593.76   168.2 2596.74   172.9 2601.96   177.7 2610.37
#Mann= 3 ,0,0
       0      .1       0   77.07    .045       0   88.01      .1       0
Bank Sta=77.07,88.01
XS Rating Curve= 0 ,0
Exp/Cntr(USF)=0,0
Exp/Cntr=0.3,0.1

Type RM Length L Ch R = 1 ,1539    ,150.8,150.8,150.8
XS GIS Cut Line= 2
2200522.67508979548744.0217005442200559.51606646548924.508808233
#Sta/Elev= 30
       0 2589.31    13.4 2577.09    21.6 2573.61      26 2571.04    29.8 2569.46
    33.8 2567.07    37.9 2563.85      42 2561.92    46.3 2561.36    54.3  2562.8
    62.4 2561.02    74.7 2559.98      91 2561.59    99.2 2563.54   103.2 2563.57
   110.7 2563.08   115.5 2561.19   123.7 2560.33   131.8 2559.56     140 2559.89
   141.3  2560.5   144.1 2562.69   148.3 2569.07   151.4 2572.79   156.3 2577.93
   160.4 2585.07     165 2591.98   168.4 2595.87   171.8 2599.09   184.2 2610.02
#Mann= 3 ,-1,0
       0      .1       0   123.7    .045       0   141.3      .1       0
#XS Ineff= 2 , 0
            54.3    2569
Permanent Ineff=
       F       F
Bank Sta=123.7,141.3
XS Rating Curve= 0 ,0
Exp/Cntr=0.3,0.1

Type RM Length L Ch R = 1 ,1388    ,115.4,115.4,115.4
XS GIS Cut Line= 2
2200330.83580707548866.6447987282200471.40320293548981.089050224
#Sta/Elev= 30
       0 2587.28     6.9 2580.69    14.1 2573.04    27.5 2559.48    37.8 2550.38
      42 2548.16      43 2547.85    48.4 2547.51    58.5 2543.56    65.3 2543.37
    73.8 2545.21    79.5 2545.93    86.4 2543.71    94.6 2543.26  101.732540.654
   105.4 2539.82   110.8  2539.9  119.962540.654   127.9 2541.76   139.2 2542.77
   143.4 2544.01   146.2 2545.44   147.8 2546.83   149.7 2549.04   153.4 2554.95
   156.5 2559.37   166.8 2578.17   168.7 2580.65   171.9 2584.14   181.3 2591.89
#Mann= 3 ,-1,0
       0      .1       0  101.73    .045       0  119.96      .1       0
Bank Sta=101.73,119.96
XS Rating Curve= 0 ,0
Exp/Cntr(USF)=0,0
Exp/Cntr=0.3,0.1

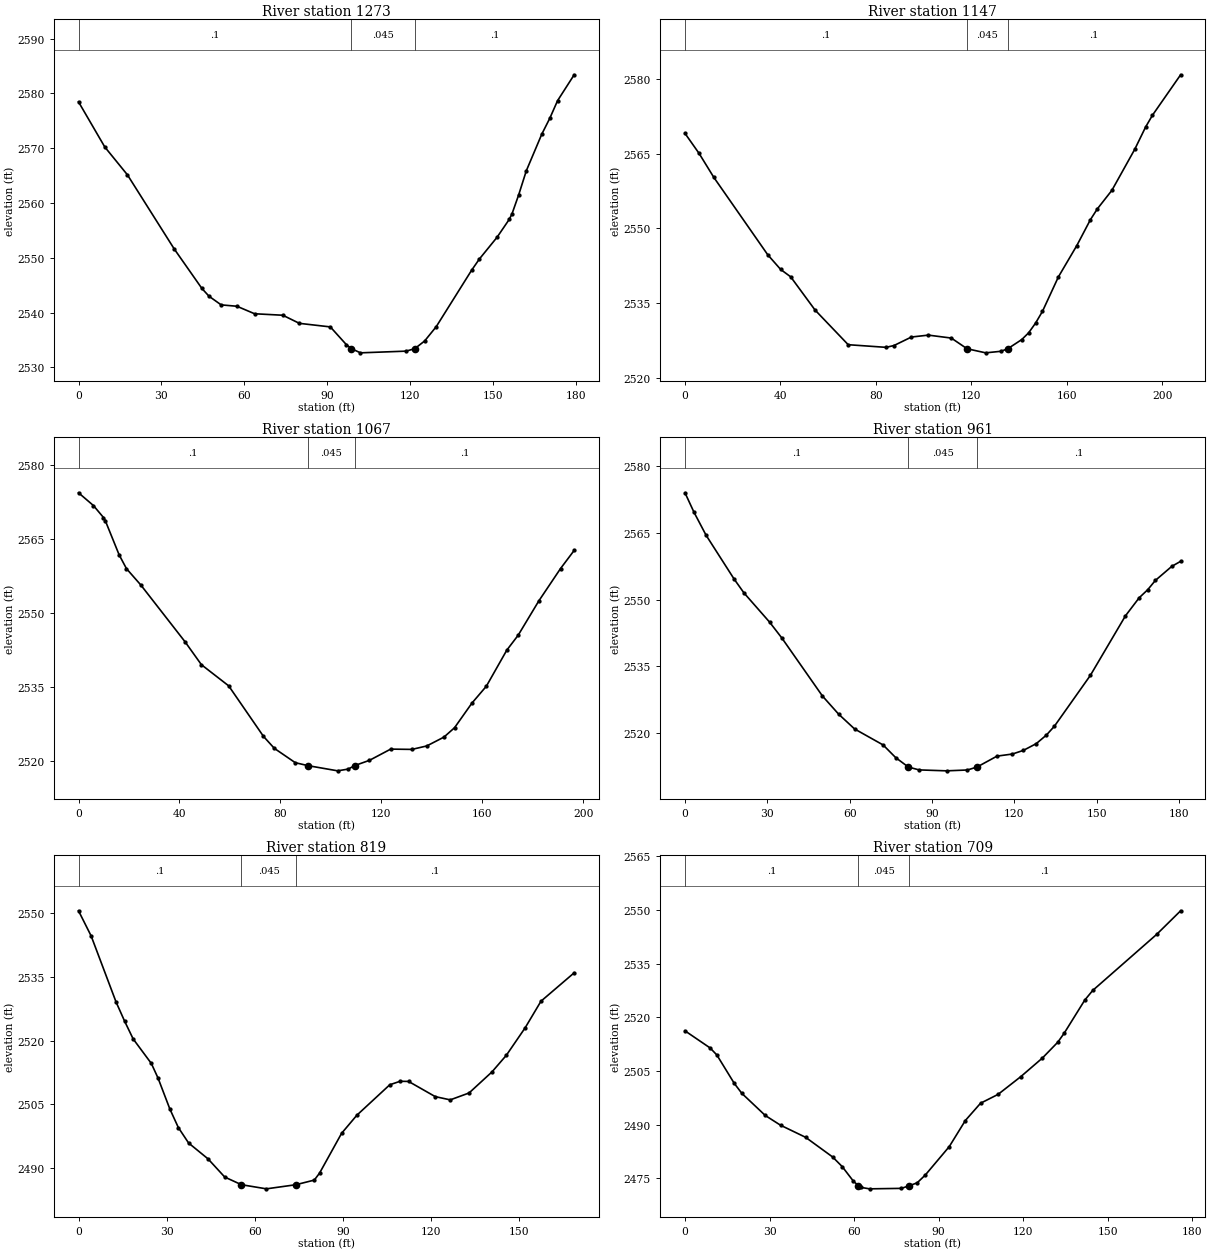
Type RM Length L Ch R = 1 ,1273    ,125.4,125.4,125.4
XS GIS Cut Line= 2
2200281.66519557548946.7273507092200404.27108957 549077.58953386
#Sta/Elev= 30
       0 2578.45     9.5 2570.22    17.7 2565.13    34.6 2551.63    44.6 2544.43
    47.2 2542.99    51.6 2541.41    57.3 2541.16    63.7 2539.79    73.9 2539.52
    79.9 2538.04    91.1 2537.39    96.9 2534.15   98.69 2533.43     102 2532.66
   118.5 2532.97  121.63 2533.42   125.2 2534.82   129.4 2537.43   142.2 2547.73
     145 2549.77   151.4 2553.74   155.8    2557   156.8    2558   159.2 2561.44
     162 2565.89   167.6 2572.57   170.5 2575.47   173.3 2578.67   179.3 2583.39
#Mann= 3 ,0,0
       0      .1       0   98.69    .045       0  121.63      .1       0
Bank Sta=98.69,121.63
XS Rating Curve= 0 ,0
Exp/Cntr(USF)=0,0
Exp/Cntr=0.3,0.1

Type RM Length L Ch R = 1 ,1147    ,80,80,80
XS GIS Cut Line= 2
2200213.44763892549020.2737667692200328.51387004549193.184103269
#Sta/Elev= 30
       0 2569.05     5.9 2565.04    12.1 2560.22    34.7 2544.71    40.1 2541.78
    44.3  2540.3    54.5 2533.65    68.4  2526.7    84.3 2526.17    87.6 2526.54
    94.9 2528.24     102 2528.62   111.6 2528.03  118.222525.886     126 2525.07
   132.4 2525.38  135.242525.886   141.1 2527.72     144 2529.08   146.9 2531.02
   149.8 2533.38   156.5 2540.31   164.2 2546.57   169.9 2551.76   172.8 2553.92
   178.9 2557.64   188.5 2565.88     193  2570.3   195.9 2572.69   207.7 2580.79
#Mann= 3 ,-1,0
       0      .1       0  118.22    .045       0  135.24      .1       0
Bank Sta=118.22,135.24
XS Rating Curve= 0 ,0
Exp/Cntr(USF)=0,0
Exp/Cntr=0.3,0.1

Type RM Length L Ch R = 1 ,1067    ,106.8,106.8,106.8
XS GIS Cut Line= 3
 2200139.2442076 549071.810131452200197.45104616549109.376247118
2200236.66841966549230.330883279
#Sta/Elev= 30
       0 2574.31     5.9 2571.73     9.9  2569.3    10.6 2568.68    16.1 2561.74
      19 2558.95    24.7 2555.63    42.2 2544.15    48.7  2539.5    59.5 2535.22
    73.3 2524.98    77.6 2522.56    85.9 2519.66   90.93 2519.06   102.7 2518.01
   106.9 2518.37   109.4 2519.07   115.3 2520.14   123.7 2522.41   132.1 2522.35
     138 2523.05   144.8 2524.84     149 2526.74   155.9 2531.73   161.6 2535.14
   169.7 2542.44   174.2 2545.46   182.4 2552.42     191 2558.97   196.4 2562.64
#Mann= 3 ,0,0
       0      .1       0   90.93    .045       0   109.4      .1       0
Bank Sta=90.93,109.4
XS Rating Curve= 0 ,0
Exp/Cntr(USF)=0,0
Exp/Cntr=0.3,0.1

Type RM Length L Ch R = 1 ,961     ,141.2,141.2,141.2
XS GIS Cut Line= 3
2200090.51813772 549126.471318212200149.70126959549230.001326286
2200195.00540861549271.328586377
#Sta/Elev= 30
       0 2574.07     3.3 2569.67     7.7 2564.51    17.9 2554.67    21.5 2551.54
    30.8    2545    35.4 2541.32    50.1 2528.35      56 2524.27    61.8 2520.95
    72.2 2517.35    76.8 2514.49    81.4 2512.38    85.3 2511.74    95.3 2511.53
   102.9 2511.72  106.42 2512.39   113.7 2514.84   119.3 2515.31   123.3 2516.13
     128 2517.65   131.7 2519.58   134.6 2521.56   147.7 2532.99   160.5  2546.4
   165.5 2550.46   168.6 2552.26   171.4 2554.36   177.4 2557.53   180.6 2558.65
#Mann= 3 ,0,0
       0      .1       0    81.4    .045       0  106.42      .1       0
Bank Sta=81.4,106.42
XS Rating Curve= 0 ,0
Exp/Cntr(USF)=0,0
Exp/Cntr=0.3,0.1

Type RM Length L Ch R = 1 ,819     ,110.8,110.8,110.8
XS GIS Cut Line= 2
2199973.70560999549245.605018221 2200104.9806076549351.698333899
#Sta/Elev= 30
       0 2550.59     4.3 2544.67    12.8  2529.1    15.7 2524.61    18.6 2520.44
    24.8 2514.66    27.1 2511.19    31.1 2503.95      34 2499.57    37.5 2495.93
    44.1 2492.21    49.8 2487.92    55.5 2486.12      64 2485.15   74.03 2486.12
    80.3 2487.21    82.1 2488.86    89.6 2498.22    94.8 2502.48     106 2509.64
   109.5 2510.46   112.4 2510.43   121.5 2506.85   126.6 2506.09     133 2507.71
   140.8 2512.66   145.7 2516.58   152.1 2523.04   157.5 2529.31   168.8 2535.99
#Mann= 3 ,0,0
       0      .1       0    55.5    .045       0   74.03      .1       0
Bank Sta=55.5,74.03
XS Rating Curve= 0 ,0
Exp/Cntr(USF)=0,0
Exp/Cntr=0.3,0.1

Type RM Length L Ch R = 1 ,709     ,199.5,199.5,199.5
XS GIS Cut Line= 2
2199939.34121699549337.4886733632200068.09099992549457.281949657
#Sta/Elev= 30
       0  2516.2     8.9 2511.43    11.3 2509.47    17.5 2501.51    20.2 2498.72
    28.5 2492.55    33.9 2489.84    42.8 2486.46    52.4 2480.96    55.8 2478.27
    59.8 2474.17   61.522472.972    62.6 2472.44    65.5 2472.06    76.8 2472.19
    79.6 2472.93    82.4 2473.74    85.3 2475.93    93.8 2483.87    99.5 2491.15
   104.9 2495.98   111.1 2498.44   119.2 2503.42   126.8 2508.57   132.3 2513.02
   134.6 2515.57   141.9 2524.81   144.7 2527.48   167.4 2543.15   175.9 2549.74
#Mann= 3 ,-1,0
       0      .1       0   61.52    .045       0    79.6      .1       0
Bank Sta=61.52,79.6
XS Rating Curve= 0 ,0
Exp/Cntr(USF)=0,0
Exp/Cntr=0.3,0.1