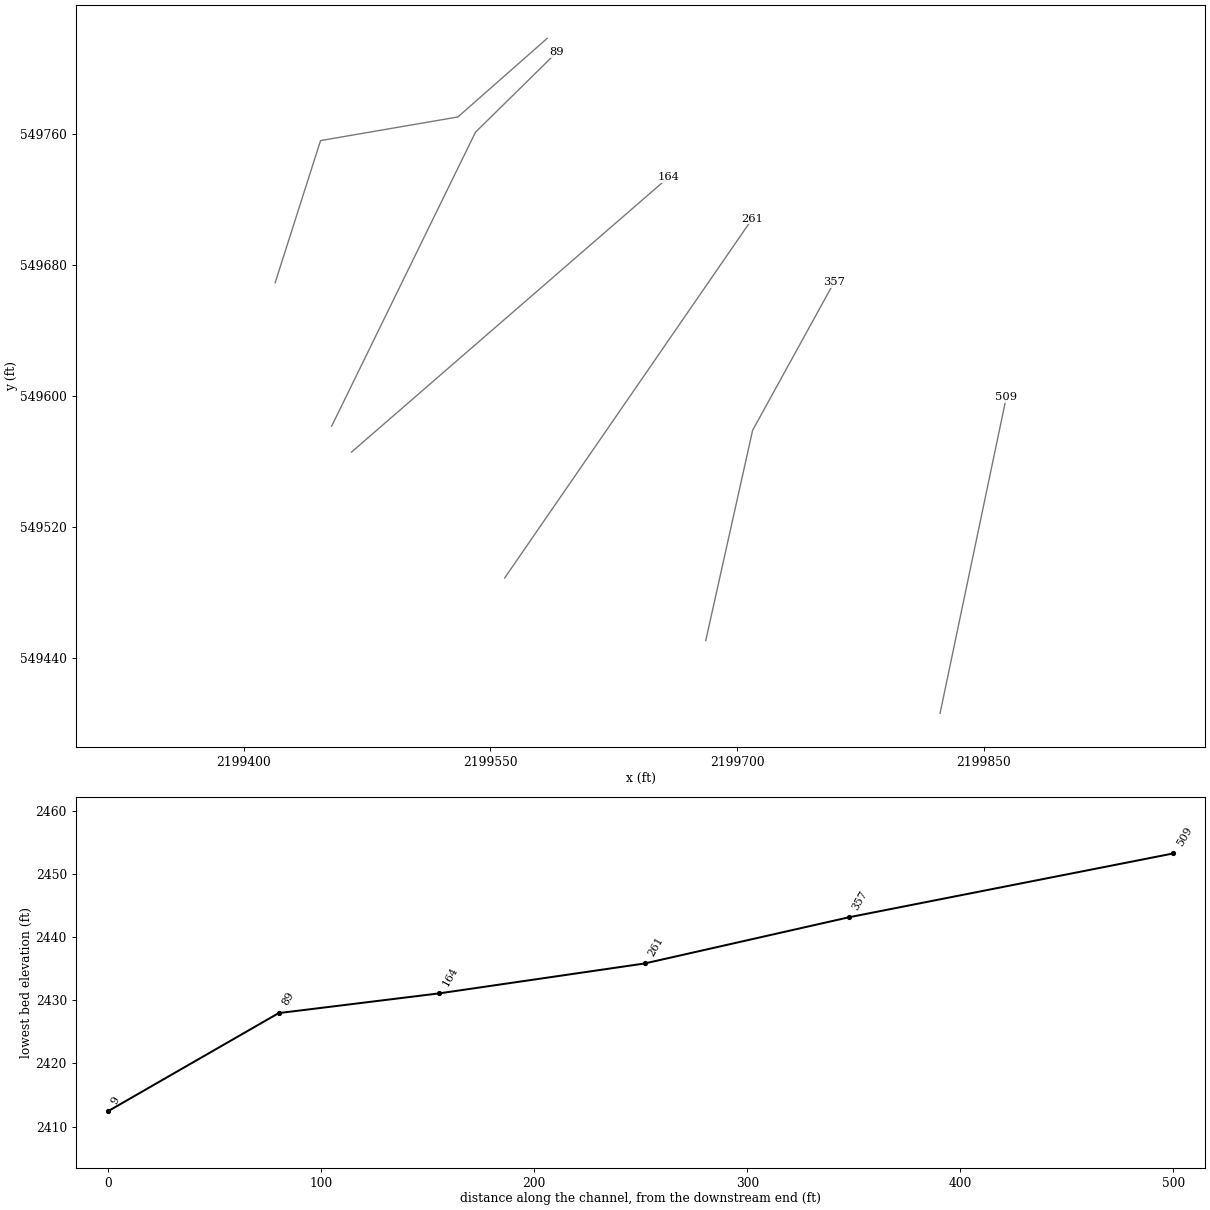
HEC-RAS study BIGRN.prj: BIGRN

--- BIGRN.g01 (geometry) --- (continued)

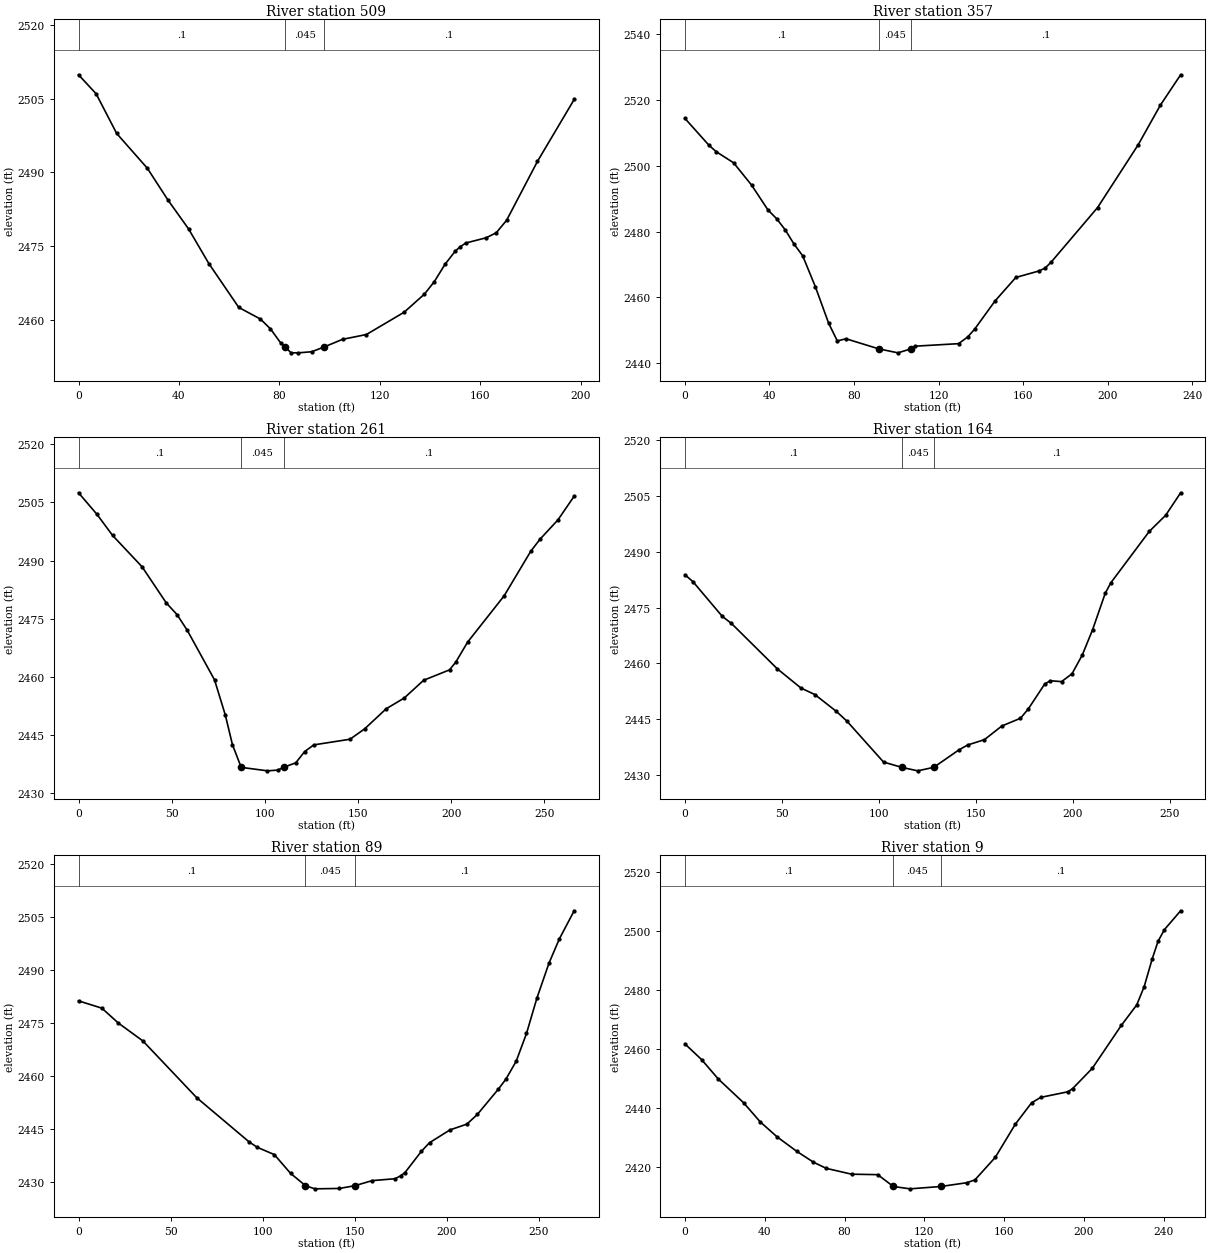
Type RM Length L Ch R = 1 ,509     ,152.2,152.2,152.2
XS GIS Cut Line= 2
2199823.46641235549406.3418181492199863.77069222549599.466492549
#Sta/Elev= 30
       0 2509.85       7 2505.99    15.2  2497.9    27.4 2490.82    35.6 2484.35
    43.8 2478.48    51.9  2471.4    63.8 2462.48    72.4 2460.12    76.4 2458.13
    80.5 2455.24   82.29 2454.43    84.6 2453.25    87.5 2453.24    92.8 2453.46
    97.7 2454.42   105.1 2455.99   114.6 2456.97   129.6  2461.5   137.7  2465.2
   141.6 2467.71   145.9 2471.27     150 2473.97   151.7 2474.73   154.1 2475.59
   162.3 2476.67   166.3 2477.69   170.4 2480.22   182.7 2492.23   197.3 2504.82
#Mann= 3 ,-1,0
       0      .1       0   82.29    .045       0    97.7      .1       0
Bank Sta=82.29,97.7
XS Rating Curve= 0 ,0
Exp/Cntr(USF)=0,0
Exp/Cntr=0.3,0.1

Type RM Length L Ch R = 1 ,357     ,96,96,96
XS GIS Cut Line= 3
2199681.02015934549450.7738037932199709.50435694549579.159100197
2199759.04209188549669.565466475
#Sta/Elev= 30
       0 2514.41    11.4 2506.23    14.8 2504.31      23 2500.94    31.5 2494.17
    39.3 2486.58    43.4 2483.92    47.5 2480.49    51.6 2476.23    55.7 2472.66
    61.7 2463.27      68 2452.14    72.1 2446.76    76.2 2447.42    91.82444.333
   100.8 2443.14  106.84 2444.33     109 2445.17   129.5 2445.93   133.8 2447.96
   137.1 2450.34   146.7 2458.87   156.6 2466.07   167.4 2468.01   170.4 2468.88
   173.3 2470.71   195.3 2487.33   214.5  2506.4     225 2518.45   234.6  2527.7
#Mann= 3 ,0,0
       0      .1       0    91.8    .045       0  106.84      .1       0
Bank Sta=91.8,106.84
XS Rating Curve= 0 ,0
Exp/Cntr(USF)=0,0
Exp/Cntr=0.3,0.1

Type RM Length L Ch R = 1 ,261     ,96.4,96.4,96.4
XS GIS Cut Line= 2
2199558.79249547549489.0501708582199709.32468397549708.365168345
#Sta/Elev= 30
       0 2507.45     9.9  2501.9    18.3 2496.45    34.1 2488.39    47.1 2479.08
    52.9 2476.05    58.4 2471.99      73 2459.25    78.8 2450.17    82.6 2442.58
    87.3 2436.72   101.4 2435.82   106.9 2436.01  110.01 2436.71   116.6 2437.89
   121.4  2440.8   126.3 2442.51   145.7 2443.96   153.6 2446.65   165.1  2451.8
   174.8 2454.58   185.2 2459.15   199.1 2461.83   202.5 2463.85   208.8 2468.97
   228.4 2480.89   242.7 2492.38   247.6 2495.45   257.3 2500.47     266 2506.57
#Mann= 3 ,0,0
       0      .1       0    87.3    .045       0  110.01      .1       0
Bank Sta=87.3,110.01
XS Rating Curve= 0 ,0
Exp/Cntr=0.3,0.1

Type RM Length L Ch R = 1 ,164     ,75.3,75.3,75.3
XS GIS Cut Line= 2
2199465.67872855 549565.903630822199658.47331079549733.772264433
#Sta/Elev= 30
       0 2483.82     4.1 2481.99    19.2 2472.66    23.9 2470.77    47.6 2458.54
    59.8 2453.37      67  2451.6    78.1 2447.07    83.5 2444.47   102.4 2433.45
   111.8 2432.03     120 2431.09  128.292432.033   141.2  2436.7   145.8 2438.05
   154.4 2439.47   163.4 2443.15     173 2445.23     177 2447.71   185.5 2454.44
   188.4 2455.33   194.2 2455.09   199.6 2457.21   204.9 2462.27   210.2 2469.05
   216.7 2478.83   219.6 2481.67   239.4 2495.48   247.9 2499.85   255.6 2505.89
#Mann= 3 ,-1,0
       0      .1       0   111.8    .045       0  128.29      .1       0
Bank Sta=111.8,128.29
XS Rating Curve= 0 ,0
Exp/Cntr(USF)=0,0
Exp/Cntr=0.3,0.1

Type RM Length L Ch R = 1 ,89      ,80.1,80.1,80.1
XS GIS Cut Line= 3
2199453.59049517549581.7406469732199541.02415289549761.209733876
2199590.59388654549810.159201175
#Sta/Elev= 30
       0 2481.16    12.7 2479.09    21.6  2474.9      35 2469.81    64.3 2453.72
    92.8 2441.21    97.2  2439.7   106.4 2437.66   115.2 2432.36   123.3 2428.87
   128.4 2427.97   141.8 2428.08   150.12428.856   159.6  2430.3     172 2430.83
     175 2431.64   177.4 2432.59   186.3 2438.59   190.7 2441.02   201.8 2444.64
     211 2446.28   216.7 2449.02   228.1 2456.17   232.2 2458.99   237.8 2464.08
   243.4 2471.93     249 2481.84   255.6 2491.81   261.2 2498.64   269.3 2506.65
#Mann= 3 ,-1,0
       0      .1       0   123.3    .045       0   150.1      .1       0
Bank Sta=123.3,150.1
XS Rating Curve= 0 ,0
Exp/Cntr(USF)=0,0
Exp/Cntr=0.3,0.1

Type RM Length L Ch R = 1 ,9       ,,,
XS GIS Cut Line= 4
 2199419.2116112549669.2412984772199446.82812277549756.088197893
2199530.34361491549770.517576116 2199584.6338937549818.526078266
#Sta/Elev= 30
       0 2461.58     8.3 2456.29    16.7 2449.69    29.4 2441.62    37.7 2435.16
    46.1  2430.1      56 2425.17    64.4 2421.47    70.8 2419.39    83.5 2417.41
    96.6 2417.25  104.422413.234   112.8 2412.44  128.282413.241   141.2 2414.51
   145.3 2415.47   155.5 2423.11   165.6 2434.41   173.7 2441.61   178.3 2443.46
     192 2445.37   194.3 2446.46   204.1 2453.28   218.7  2467.9   226.4 2474.81
   230.1 2480.96   234.2 2490.53   237.1 2496.42   240.3 2500.37   248.4 2506.74
#Mann= 3 ,-1,0
       0      .1       0  104.42    .045       0  128.28      .1       0
Bank Sta=104.42,128.28
XS Rating Curve= 0 ,0
Exp/Cntr(USF)=0,0
Exp/Cntr=0.3,0.1
LCMann Table=0

Chan Stop Cuts=-1
Use User Specified Reach Order=0
Composite Channel Slope=5